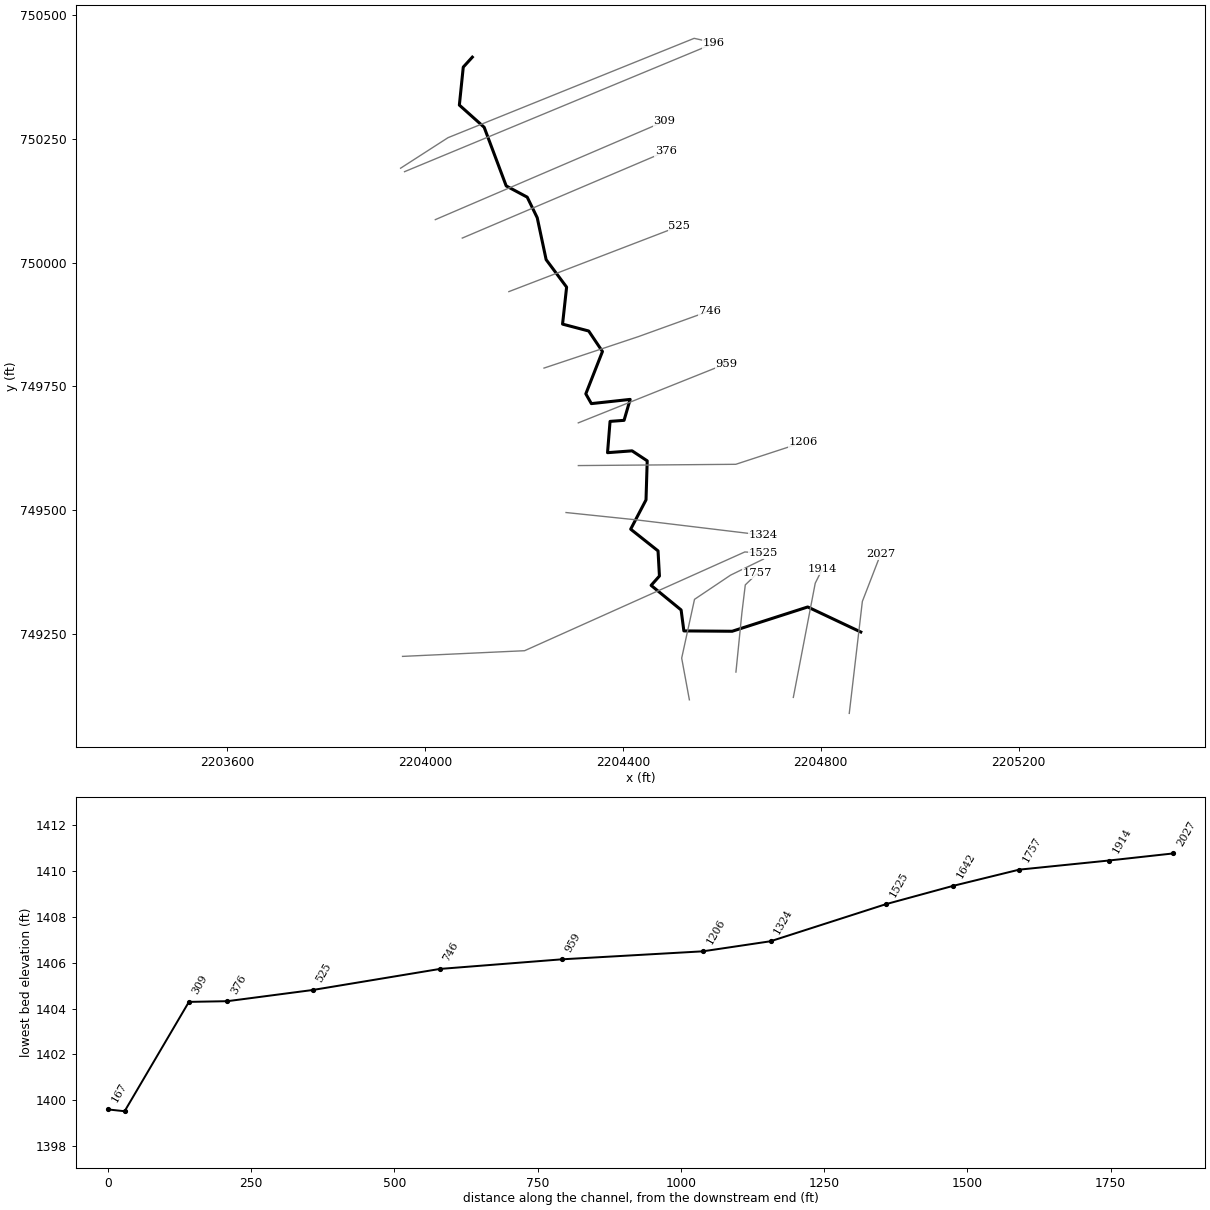
--- PECKSRNT2A.prj (project) ---

Proj Title=PECKSRNT2A
Current Plan=p01
Default Exp/Contr=0,0
English Units
Geom File=g01
Flow File=f01
Plan File=p01
BEGIN DESCRIPTION:
---------- MODELED AS PART OF WVEMD CTP PROGRAM, 2023----------
Stream Name: Pecks Run Tributary 2A
Flood Zone:  AFH
Upshur County, WV
HEC-RAS Version: RAS 6.3
Vertical Datum: NAVD88
Projection: NAD 1983 StatePlane West Virginia S FIPS 4702 (US Feet)
Terrain: 1-meter LIDAR (FEMA Region III 3DEP collected 2016-2018)
Land Use: 2019 NLCD
Hydrologic Method:
WV SIR2010-5033 regression equations
Additional Model Notes:
Coincident peak with PECKSRNT2
END DESCRIPTION:
DSS Export Rating Curves= 0
DSS Export Rating Curve Sorted= 0
DSS Export Volume Flow Curves= 0
DXF OffsetX= 0
DXF OffsetY= 0
DXF ScaleX= 0
DXF ScaleY= 0

--- PECKSRNT2A.p01 (plan) ---

Plan Title=Floodplain
Program Version=6.30
Short Identifier=Floodplain
Geom File=g01
Flow File=f01
Subcritical Flow
K Sum by GR= 0
Std Step Tol= 0.01
Critical Tol= 0.01
Num of Std Step Trials= 20
Max Error Tol= 0.3
Flow Tol Ratio= 0.001
Split Flow NTrial= 30
Split Flow Tol= 0.02
Split Flow Ratio= 0.02
Log Output Level= 0
Friction Slope Method= 1
Unsteady Friction Slope Method= 2
Unsteady Bridges Friction Slope Method= 1
Parabolic Critical Depth
Global Vel Dist= 0 , 0 , 0
Global Log Level= 0
CheckData=False
Encroach Param=-1 ,0,0, 0
Mapping Interval=1HOUR
Computation Time Step Use Courant=        0
Computation Time Step Use Time Series=    0
Computation Time Step Count To Double=0
Computation Time Step Max Doubling=0
Computation Time Step Max Halving=0
Computation Time Step Residence Courant=0
Run HTab= 0
Run UNet= 0
Run Sediment= 0
Run PostProcess= 0
Run WQNet= 0
Run RASMapper=-1
UNET Theta= 0
UNET Theta Warmup= 0
UNET ZTol= 0
UNET ZSATol= 0
UNET MxIter= 0
UNET Max Iter WO Improvement= 0
UNET MaxInSteps= 0
UNET DtIC= 0
UNET DtMin= 0
UNET MaxCRTS= 0
UNET WFStab= 0
UNET SFStab= 0
UNET WFX= 1
UNET SFX= 1
UNET Gravity=32.17405
UNET 1D Methodology=Finite Difference
UNET DSS MLevel= 1
UNET Pardiso=0
UNET DZMax Abort= 0
UNET Use Existing IB Tables= 0
UNET Froude Reduction=False
UNET Froude Limit= 0
UNET Froude Power= 0
UNET D1 Cores= 0
UNET WindReference=Eulerian
UNET WindDragFormulation=Hsu (1988)
UNET D2 Coriolis=0
UNET D2 Cores= 0
UNET D2 Theta= 1
UNET D2 Theta Warmup= 1
UNET D2 Z Tol= 0.01
UNET D2 Volume Tol= 0.01
UNET D2 Max Iterations= 20
UNET D2 Equation= 0
UNET D2 RampUpFraction=0.1
UNET D2 TimeSlices= 1
UNET D2 Turbulence Formulation=Non-Conservative (original)
UNET D2 Eddy Viscosity=0.3
UNET D2 Transverse Eddy Viscosity=0.1
UNET D2 Smagorinsky Mixing=0
UNET D2 BCVolumeCheck=0
UNET D2 Cores=0
UNET D2 SolverType=PARDISO (Direct)
UNET D2 Minimum Iterations= 3
UNET D2 Maximum Iterations= 30
UNET D2 Restart Number= 10
UNET D2 Relaxation Coeff=1.3
UNET D2 SOR Precondition Iterations= 10
UNET D2 ILUT Maximum Fill= 8
UNET D2 ILUT Tolerance=1E-08
UNET D2 Convergence Tolerance=0.00001
UNET D1D2 MaxIter= 0
UNET D1D2 ZTol=0.01
UNET D1D2 QTol=0.1
UNET D1D2 MinQTol=1
Write IC File= 0
Write IC File at Fixed DateTime=0
Write IC File at Sim End=0
Echo Input=False
Echo Parameters=False
Echo Output=False
Write Detailed= 0
HDF Write Warmup=0
HDF Write Time Slices=0
HDF Flush=0
HDF Compression= 1
HDF Chunk Size= 1
HDF Spatial Parts= 1
HDF Use Max Rows=0
HDF Fixed Rows= 1
Calibration Method= 0
Calibration Iterations= 20
Calibration Max Change=0.05
Calibration Tolerance=0.2
Calibration Maximum=1.5
Calibration Minimum=0.5
Calibration Optimization Method= 1
WQ AD Non Conservative
WQ ULTIMATE=-1
WQ Max Comp Step=1HOUR
WQ Output Interval=15MIN
WQ Output Selected Increments= 0
WQ Output face flow=0
WQ Output face velocity=0
WQ Output face area=0
WQ Output face dispersion=0
WQ Output cell volume=0
WQ Output cell surface area=0
WQ Output cell continuity=0
WQ Output cumulative cell continuity=0
WQ Output face conc=0
WQ Output face dconc_dx=0
WQ Output face courant=0
WQ Output face peclet=0
WQ Output face adv mass=0
WQ Output face disp mass=0
WQ Output cell mass=0
WQ Output cell source sink temp=0
WQ Output nsm pathways=0
WQ Output nsm derived pathways=0
WQ Create Restart=0
WQ Fixed Restart=0
WQ System Summary=0
WQ Write To DSS=0
Sorting and Armoring Iterations= 10
XS Update Threshold= 0.02
Bed Roughness Predictor= 0
Hydraulics Update Threshold= 0.02
Energy Slope Method= 1
Volume Change Method= 1
Sediment Retention Method= 0
Sediment TS Multiplier= 1
Warm Up Method= 0
XS Weighting Method= 0
Number of US Weighted Cross Sections= 1
Number of DS Weighted Cross Sections= 1
Upstream XS Weight=0
Main XS Weight=1
Downstream XS Weight=0
Number of DS XS's Weighted with US Boundary= 1
Upstream Boundary Weight= 1
Weight of XSs Associated with US Boundary= 0
Number of US XS's Weighted with DS Boundary= 1
Downstream Boundary Weight= 0.5
Weight of XSs Associated with DS Boundary= 0.5
Percentile Method= 0
Sediment Output Level= 3
Mass or Volume Output= 0
Output Increment Type= 1
Profile and TS Output Increment= 1
Transport Output Increment 1
XS Output Flag= 0
XS Output Increment= 10
Read HDF5 Sediment Hotstart= 0
Sediment Hotstart Type= 0
Write Gradation File= 0
Read Gradation Hotstart= 0
Write HDF5 File= 1
Write Binary Output= 1
Write DSS Sediment File= 0
DSS Sediment Output Type= 1
SV Curve= 0
Specific Gage Flag= 0
Subcell Erosion Methods= 0
Subcell Deposition Methods= 0
Advection Scheme= 1
Matrix Solver= 0
Implicit Weighting Factor= 1
Maximum Outer Loop Convergence Iterations= 5
Convergence Maximum Absolute= 0.001
Convergence RMSE= 0.0001
Grain Fractions Max Abs Error= 0.001
Max Subgrid Regions= 1
Max Subgrid Length Scale= 3.402823E+38
Initial Layer Thickness= 3.402823E+38
Min Layer Thickness= 3.402823E+38
Max Layer Thickness= 3.402823E+38
Number of Layers= 5

--- PECKSRNT2A.f01 (steady flow) ---

Flow Title=Flows
Program Version=6.31
Number of Profiles= 1
Profile Names=01pct
River Rch & RM=PECKSRNT2A,Main            ,2027
     237
Boundary for River Rch & Prof#=PECKSRNT2A,Main            , 1
Up Type= 0
Dn Type= 3
Dn Slope=0.00073
DSS Import GetInterval= 0
DSS Import GetPeak= 0
DSS Import FillOption= 0

--- PECKSRNT2A.g01 (geometry) ---

Geom Title=Geometry
Program Version=6.31

River Reach=PECKSRNT2A      ,Main
Reach XY= 30
2204880.88396772749253.5017082542204773.60603299749304.154780464
2204620.88006215   749255.0481272204523.17845327749255.732535293
2204517.60418859749298.1201729132204456.97693905749347.799874226
2204473.80425053749366.7175349612204470.95631596749417.525057428
2204415.66139098749461.4430636162204446.64196329749520.617645691
2204449.06625519749599.5832719642204418.46216599749619.808923241
 2204368.8744365749616.0927467932204373.94286985749679.322373313
2204402.26852418749681.4804972792204414.62404001749723.799150028
2204336.17142609749715.282912332 2204324.9454764749735.025099717
2204358.59414373749820.6464106052204330.75891729749862.090081458
 2204277.9247707749876.0088496512204286.11580145749950.796400726
2204244.71944892750006.3551906112204226.71499876750091.100269234
2204206.47622664750132.7018383112204163.97555735750155.416228861
     2204119.437      750273.981 2204069.2891598750318.831271465
2204077.18399644750395.6382762352204095.50866383750415.729184114

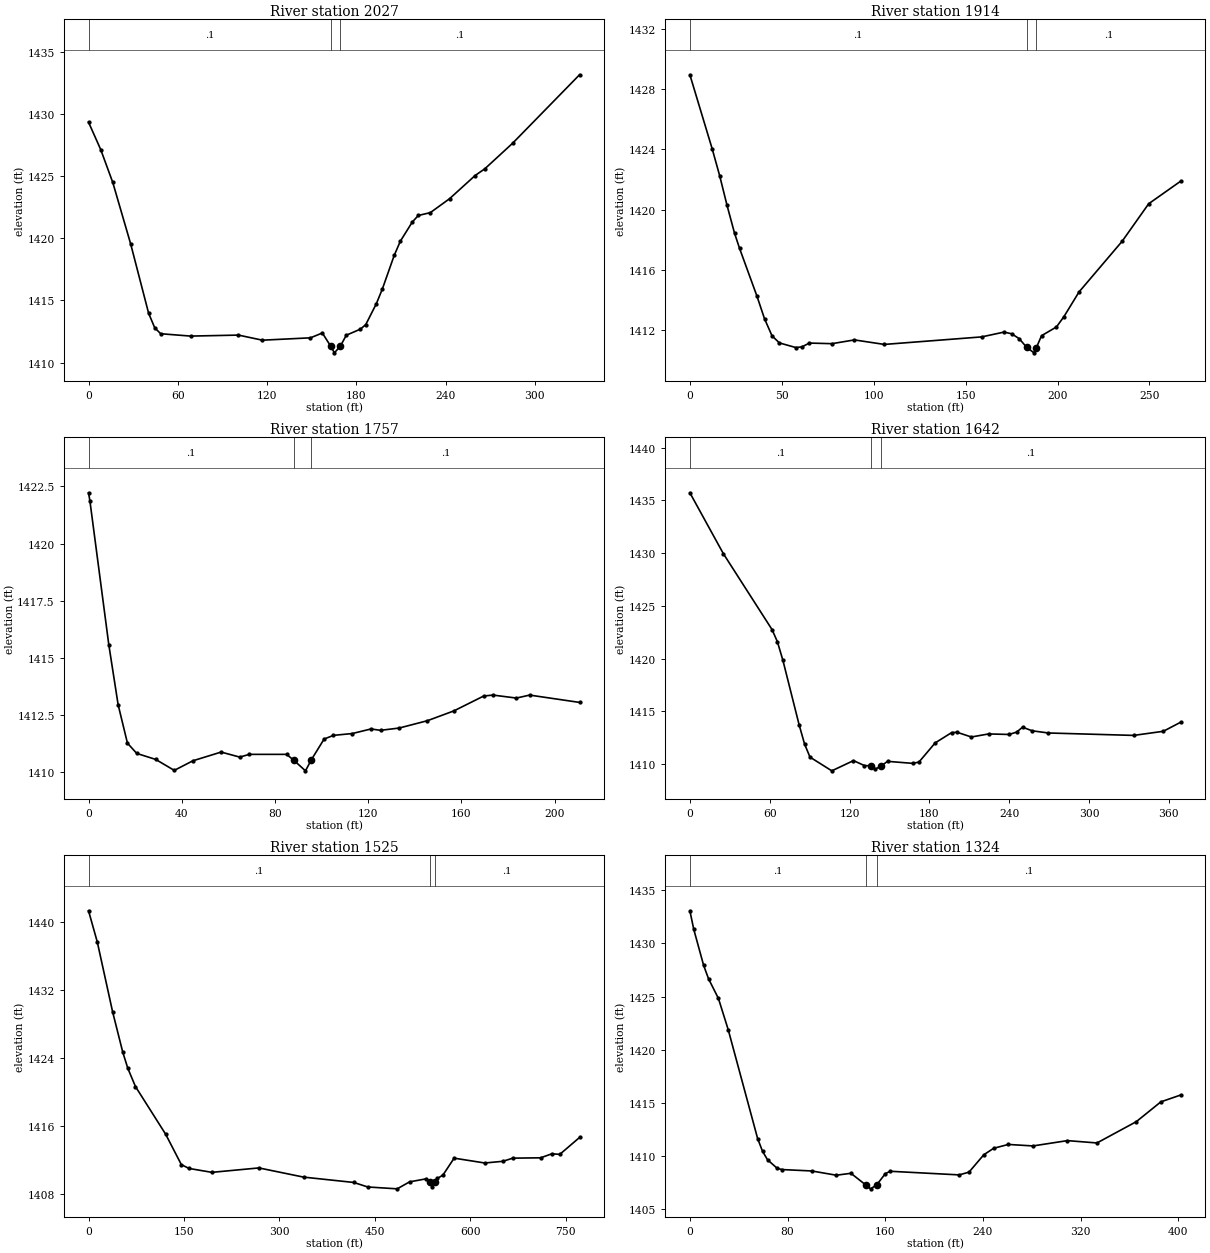
Type RM Length L Ch R = 1 ,2027    ,112.4,112.4,112.4
XS GIS Cut Line= 3
2204857.57446957749089.0255271882204884.03565007749315.338255181
2204920.94203341749410.737774367
#Sta/Elev= 30
       0 1429.37     8.2 1427.16    16.3 1424.51    28.3 1419.57    40.4 1413.97
    44.5  1412.8    48.5 1412.32    68.6 1412.13   100.8 1412.21   116.9  1411.8
   149.2 1411.99   157.2 1412.38   162.81411.318   165.3 1410.78   169.3 1411.32
   173.3  1412.2   182.8 1412.69   186.4 1413.06   193.5 1414.74   197.5 1415.91
   205.5 1418.63   209.6 1419.77   217.6 1421.31   221.7 1421.85   229.8 1422.08
   242.7  1423.2   259.9 1425.07   266.5 1425.62   285.1 1427.67   330.1 1433.19
#Mann= 3 ,-1,0
       0      .1       0   162.8    .045       0   169.3      .1       0
Bank Sta=162.8,169.3
XS Rating Curve= 0 ,0
Exp/Cntr(USF)=0,0
Exp/Cntr=0.3,0.1

Type RM Length L Ch R = 1 ,1914    ,155.6,156.8,155.6
XS GIS Cut Line= 3
2204744.47426228749121.3097087612204788.78822872749352.251853812
2204803.12214188749380.818924756
#Sta/Elev= 30
       0 1428.97    12.1 1424.06    16.2 1422.26    20.2 1420.29    24.3 1418.43
      27 1417.43    36.5 1414.24    40.6 1412.74    44.7  1411.6    48.7 1411.13
    57.7 1410.82      61 1410.87      65 1411.12    77.3 1411.08    89.5 1411.33
   105.8 1411.03   158.7 1411.53   170.9 1411.85     175 1411.74   179.1 1411.42
   183.2 1410.84   187.2 1410.47   188.51410.815   191.3 1411.61   199.4 1412.19
   203.5 1412.88   211.7 1414.52   235.2  1417.9   249.6 1420.39   267.1  1421.9
#Mann= 3 ,-1,0
       0      .1       0   183.2    .045       0   188.5      .1       0
Bank Sta=183.2,188.5
XS Rating Curve= 0 ,0
Exp/Cntr(USF)=0,0
Exp/Cntr=0.3,0.1

Type RM Length L Ch R = 1 ,1757    ,115,115.5,113.3
XS GIS Cut Line= 4
2204628.45501571749172.5655336762204640.49064037749292.062092807
2204647.36814018749348.801466208 2204671.4393895749372.013028053
#Sta/Elev= 29
       0 1422.22      .6 1421.86     8.7 1415.58    12.7 1412.96    16.7 1411.28
    20.7 1410.83    28.8 1410.57    36.8 1410.09    44.8 1410.51    56.9 1410.89
    64.9 1410.67      69 1410.79      85 1410.79      88 1410.54    93.1 1410.07
    95.61410.551   101.1 1411.46   105.1 1411.62   113.2  1411.7   121.2  1411.9
   125.3 1411.84   133.3 1411.94   145.4 1412.26   156.8 1412.69   169.6 1413.34
   173.6 1413.38   183.6 1413.25   189.3 1413.38   210.7 1413.06
#Mann= 3 ,-1,0
       0      .1       0      88    .045       0    95.6      .1       0
Bank Sta=88,95.6
XS Rating Curve= 0 ,0
Exp/Cntr(USF)=0,0
Exp/Cntr=0.3,0.1

Type RM Length L Ch R = 1 ,1642    ,124.5,117.2,108.1
XS GIS Cut Line= 5
2204534.32536973749116.4241996022204518.76749068749200.711701632
2204544.69939892749319.5785716082204617.64874414749368.531293777
2204684.07150264749400.910508815
#Sta/Elev= 30
       0 1435.73    25.2 1429.95    61.8 1422.75    65.8  1421.6    69.9 1419.86
    82.1 1413.74    86.2 1411.91    90.3 1410.66   106.7 1409.36     123 1410.33
   131.2 1409.86136.23951409.832   139.4 1409.52143.53951409.804   148.6 1410.26
   167.4 1410.07   172.2 1410.19   184.4 1412.01   196.7 1412.98   200.8 1413.02
   211.6 1412.57   224.6 1412.86   239.9 1412.81   245.6 1413.03   250.1  1413.5
   257.2 1413.16   269.4 1412.95   333.6 1412.72   355.9 1413.11   369.1 1413.98
#Mann= 3 ,-1,0
       0      .1       0136.2395    .045       0143.5395      .1       0
Bank Sta=136.2395,143.5395
XS Rating Curve= 0 ,0
Exp/Cntr(USF)=0,0
Exp/Cntr=0.3,0.1

Type RM Length L Ch R = 1 ,1525    ,201.8,201.2,191
XS GIS Cut Line= 4
2203954.42658762749204.2365273192204201.14911322749215.711993626
2204646.39720592749415.3851073652204683.11869811749413.090014104
#Sta/Elev= 30
       0 1441.27    13.8 1437.59    37.8  1429.4    53.8 1424.64    61.8 1422.73
    73.8 1420.59   121.2 1414.99   145.9 1411.41   157.9 1410.96   193.9  1410.5
   267.8 1411.02     338 1409.94     417 1409.31   438.8 1408.78   485.2 1408.56
   504.6 1409.38   530.9 1409.74   536.2 1409.36   539.6  1408.8   544.2 1409.33
   548.4 1409.78   557.2 1410.19   574.7 1412.17   622.9  1411.6   651.4  1411.8
   666.8 1412.17   710.6 1412.21   728.6 1412.69   740.7 1412.61   771.8  1414.6
#Mann= 3 ,-1,0
       0      .1       0   536.2    .045       0   544.2      .1       0
Bank Sta=536.2,544.2
XS Rating Curve= 0 ,0
Exp/Cntr(USF)=0,0
Exp/Cntr=0.3,0.1

Type RM Length L Ch R = 1 ,1324    ,115.9,118.1,118.6
XS GIS Cut Line= 3
2204284.94758018749495.0781584652204426.90372316749480.296061644
2204684.41082236 749449.26627257
#Sta/Elev= 30
       0 1433.06     3.2 1431.31    11.3 1427.92    15.3 1426.67    23.4 1424.82
    31.4 1421.89    55.5 1411.66    59.5 1410.47    63.6 1409.67    71.6 1408.86
    75.6 1408.75    99.8 1408.62   119.9 1408.22   131.9  1408.4     144 1407.31
     148 1406.94     1531407.314   160.1 1408.37   164.1 1408.59   220.6 1408.25
   228.6 1408.51   240.7 1410.14   248.8 1410.75   260.8 1411.11     281 1410.97
   309.2 1411.47   333.4 1411.25   365.6 1413.25   385.7 1415.11   402.1 1415.76
#Mann= 3 ,-1,0
       0      .1       0     144    .045       0     153      .1       0
Bank Sta=144,153
XS Rating Curve= 0 ,0
Exp/Cntr(USF)=0,0
Exp/Cntr=0.3,0.1

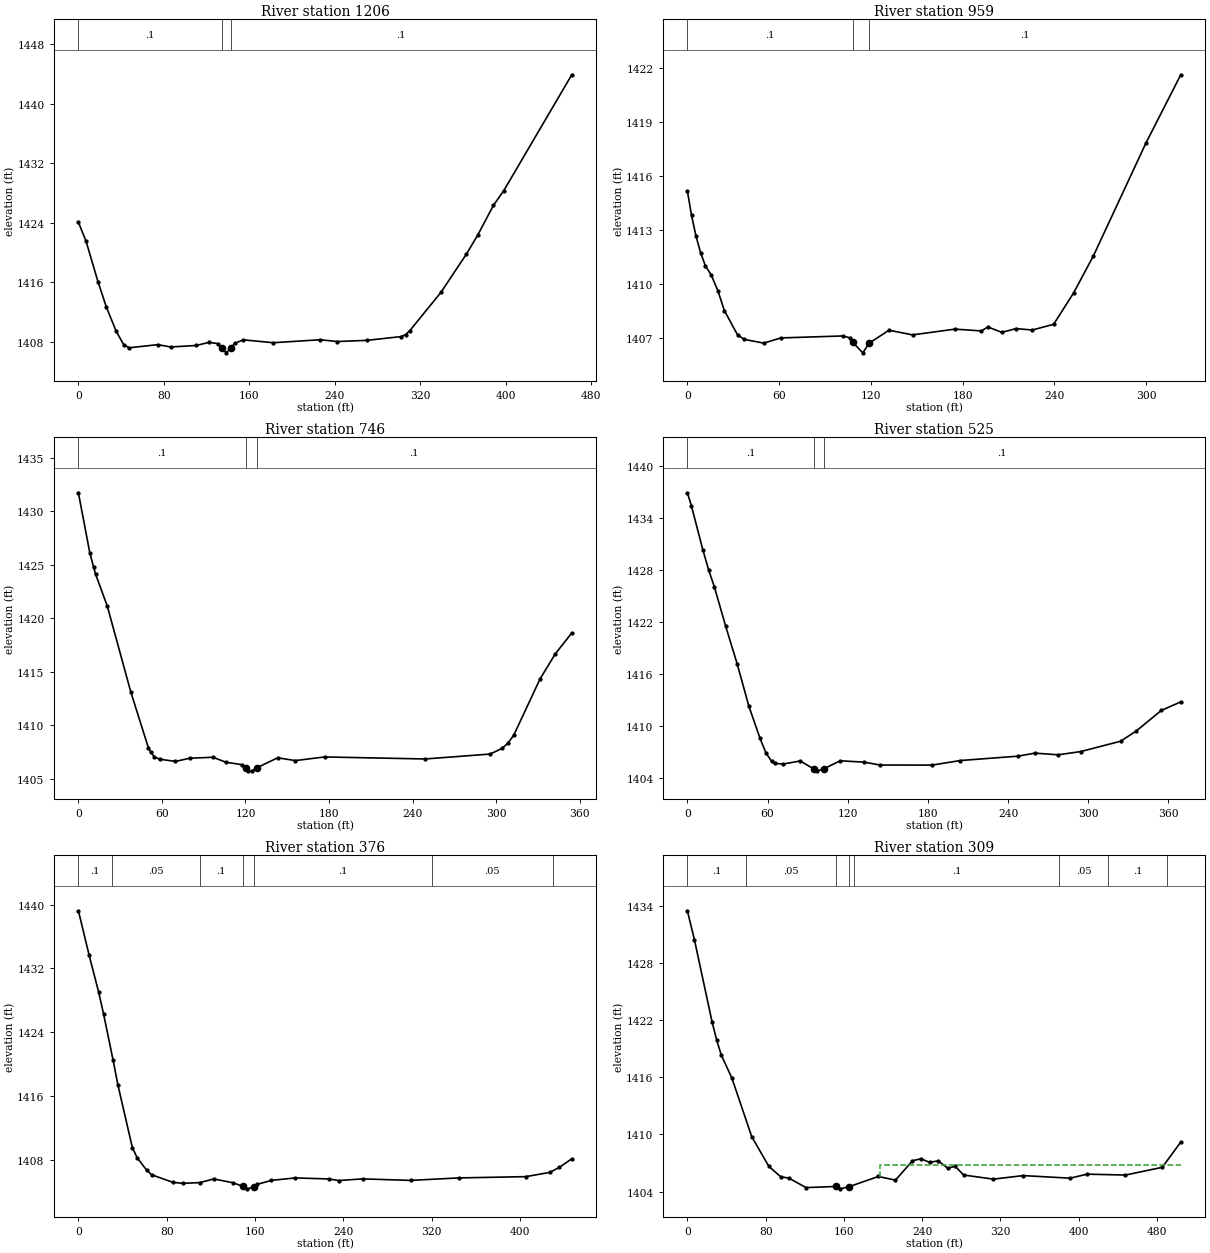
Type RM Length L Ch R = 1 ,1206    ,233.8,246.1,230
XS GIS Cut Line= 3
2204309.87400222749590.022478577 2204628.1275991749592.585379528
 2204764.5203528749637.198656572
#Sta/Elev= 30
       0 1424.06     7.2 1421.49    18.3 1416.08    26.3  1412.6    35.4  1409.4
    42.3 1407.62    47.5 1407.18    74.3  1407.6    86.3 1407.29   110.3 1407.49
   122.3 1407.91   130.3 1407.75   134.3 1407.16   138.3  1406.5   142.51407.115
   146.3 1407.77   154.3 1408.25   182.3 1407.86   226.3 1408.26   242.3 1408.02
   270.3 1408.18   302.3 1408.69   306.3 1408.96   310.3  1409.5   339.4 1414.64
   363.2 1419.78   373.7 1422.31   388.5 1426.33   398.1 1428.29   461.8 1443.88
#Mann= 3 ,-1,0
       0      .1       0   134.3    .045       0   142.5      .1       0
Bank Sta=134.3,142.5
XS Rating Curve= 0 ,0
Exp/Cntr(USF)=0,0
Exp/Cntr=0.3,0.1

Type RM Length L Ch R = 1 ,959     ,208.8,212.8,209.6
XS GIS Cut Line= 2
2204309.70702448749676.3372111832204609.21669509749796.141079426
#Sta/Elev= 30
       0 1415.16     2.7 1413.81     5.6 1412.66     8.7 1411.71    11.8 1410.99
    15.6 1410.48    19.9 1409.62    24.2  1408.5    32.8 1407.15    37.1  1406.9
      50 1406.69      61 1406.98   101.7 1407.09   106.1 1406.99   108.11406.734
   114.7 1406.15     119  1406.7   131.9 1407.41   147.2 1407.15     175 1407.47
   192.2 1407.37   196.5 1407.59   205.6 1407.29   214.9  1407.5   225.5 1407.42
   239.5 1407.74   252.5 1409.48   265.5 1411.55   299.9 1417.84   322.6 1421.63
#Mann= 3 ,-1,0
       0      .1       0   108.1    .045       0     119      .1       0
Bank Sta=108.1,119
XS Rating Curve= 0 ,0
Exp/Cntr(USF)=0,0
Exp/Cntr=0.3,0.1

Type RM Length L Ch R = 1 ,746     ,219,221.7,219.7
XS GIS Cut Line= 3
2204240.41381847749787.1271428462204431.45547975749850.807696607
2204575.32636047749902.695555225
#Sta/Elev= 30
       0 1431.75     8.2 1426.12    10.9 1424.81    12.4 1424.12    20.8 1421.12
    37.7 1413.08    50.3 1407.87      52 1407.48    54.6 1407.02    58.4 1406.82
    69.7 1406.61    79.9 1406.91    96.7    1407   105.8 1406.54   117.8  1406.3
   120.3 1405.98     122 1405.73   124.8 1405.73   127.9    1406   143.1 1406.95
   155.8 1406.69   176.8 1407.03   248.9 1406.84   295.7  1407.3   304.2 1407.83
   308.4 1408.31   312.7 1409.08   331.6 1414.35   342.5 1416.68   354.3 1418.63
#Mann= 3 ,-1,0
       0      .1       0   120.3    .045       0   127.9      .1       0
Bank Sta=120.3,127.9
XS Rating Curve= 0 ,0
Exp/Cntr(USF)=0,0
Exp/Cntr=0.3,0.1

Type RM Length L Ch R = 1 ,525     ,145.4,149.2,148.5
XS GIS Cut Line= 2
2204169.36010431749941.7057443422204514.09478209750074.097615609
#Sta/Elev= 30
       0 1436.87       3 1435.38    11.6 1430.28    15.9 1427.99    20.2 1426.02
    28.7 1421.47    37.3 1417.13    45.9 1412.32    54.4 1408.55    58.7 1406.92
      63 1405.91    65.5 1405.67    71.6 1405.59    84.4 1405.95    94.6 1405.04
    97.3 1404.81     1021405.035   114.4 1405.97   132.4 1405.81   144.2 1405.48
     183 1405.47   204.4    1406   247.3  1406.5   260.1 1406.85   277.5 1406.66
   294.4 1407.03   324.4 1408.23   336.1 1409.42   354.7 1411.77   369.3 1412.76
#Mann= 3 ,-1,0
       0      .1       0    94.6    .045       0     102      .1       0
Bank Sta=94.6,102
XS Rating Curve= 0 ,0
Exp/Cntr(USF)=0,0
Exp/Cntr=0.3,0.1

Type RM Length L Ch R = 1 ,376     ,66.6,67,66.8
XS GIS Cut Line= 2
2204075.20838086 750049.974604242204486.58319876750224.998396107
#Sta/Elev= 30
       0 1439.22     9.7 1433.66    18.4 1428.99    22.8 1426.28    31.5 1420.43
    35.8 1417.36    48.9  1409.5    53.2 1408.23    61.9 1406.66    66.3 1406.09
    85.5 1405.14    94.7 1405.01   109.9  1405.1   122.8 1405.56   140.2 1405.08
   148.8 1404.64   153.2 1404.32   158.7 1404.57   161.9 1404.88   174.9 1405.38
   196.7 1405.69   227.1 1405.56   235.8 1405.36   257.5 1405.57     301 1405.38
   344.5 1405.69   405.3 1405.85   427.1 1406.38   435.7    1407   447.1 1408.09
#Mann= 7 ,-1,0
       0      .1       0      30     .05       0     110      .1       0
   148.8    .045       0   158.7      .1       0     320     .05       0
     430      .1       0
Bank Sta=148.8,158.7
XS Rating Curve= 0 ,0
Exp/Cntr(USF)=0,0
Exp/Cntr=0.3,0.1

Type RM Length L Ch R = 1 ,309     ,111.9,112.2,112.5
XS GIS Cut Line= 2
2204020.66361603750087.2395889712204484.15214604750286.051774211
#Sta/Elev= 30
       0 1433.49     7.2 1430.45    25.2 1421.84    29.9 1419.93    34.6 1418.35
    45.5 1415.92    65.8 1409.76    83.3 1406.65    95.2 1405.57   103.9 1405.41
   121.3 1404.42   151.8 1404.54   156.4 1404.29   165.6 1404.53   195.3 1405.59
   212.7  1405.2   230.1 1407.24   238.7 1407.45   247.6 1407.07   256.3 1407.23
   266.1 1406.46   273.7 1406.66   282.4 1405.74   312.8 1405.31   343.3 1405.68
   391.2 1405.41   408.6 1405.83   447.8 1405.74   485.4 1406.55   504.3  1409.2
#Mann= 8 ,-1,0
       0      .1       0      60     .05       0   151.8    .045       0
   165.6     .05       0     170      .1       0     380     .05       0
     430      .1       0     490     .05       0
#XS Ineff= 2 , 0
                          196.39         1406.76
Permanent Ineff=
       F       F
Bank Sta=151.8,165.6
XS Rating Curve= 0 ,0
Exp/Cntr(USF)=0,0
Exp/Cntr=0.3,0.1

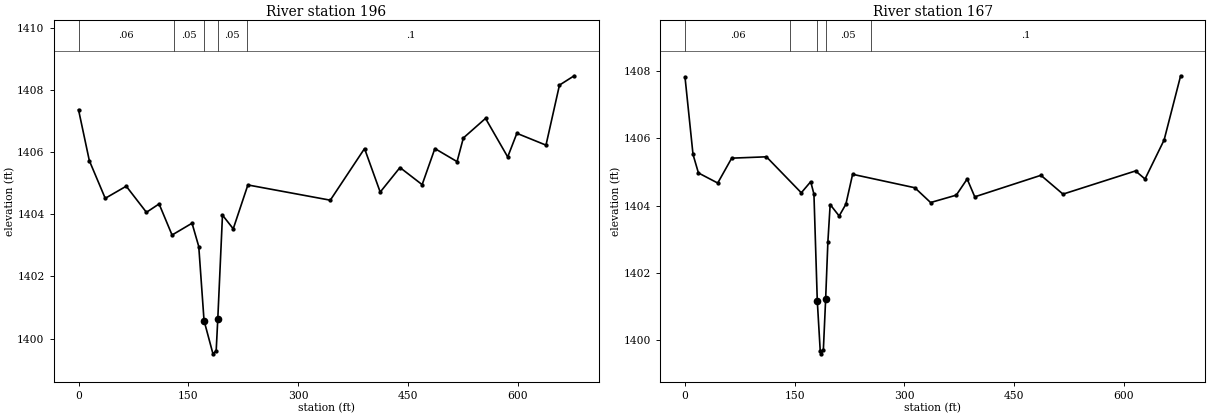
Type RM Length L Ch R = 1 ,196     ,29.3,29.4,29.3
XS GIS Cut Line= 2
2203958.45857648750184.2062682762204584.02574593750443.619130155
#Sta/Elev= 30
       0 1407.36    14.8 1405.72    36.5 1404.51    65.2  1404.9    92.8 1404.06
   110.1 1404.33   127.8 1403.33   155.1 1403.71   164.3 1402.96   171.5 1400.58
   183.7 1399.51   188.1 1399.61190.26081400.616   196.7 1403.97   211.4 1403.53
   231.4 1404.94     344 1404.45   390.8 1406.11   412.2 1404.71   439.2  1405.5
   469.5 1404.95   486.9 1406.11   517.2 1405.69   525.8 1406.45   556.1 1407.08
   586.4 1405.84   598.9  1406.6   638.7 1406.22   657.1 1408.15   677.2 1408.45
#Mann= 5 ,-1,0
       0     .06       0     130     .05       0   171.5    .045       0
190.2608     .05       0     230      .1       0
Bank Sta=171.5,190.2608
XS Rating Curve= 0 ,0
Exp/Cntr(USF)=0,0
Exp/Cntr=0.3,0.1

Type RM Length L Ch R = 1 ,167     ,,,
XS GIS Cut Line= 4
2203950.48670241750191.2339638172204046.28329802750252.908818846
 2204543.9704174750453.7860110282204570.64102628750447.857162356
#Sta/Elev= 30
       0 1407.83      11 1405.52    18.4 1404.97    44.8 1404.67    63.9 1405.41
   111.4 1405.45   159.1 1404.38     172 1404.71   176.4 1404.34180.9983 1401.16
     185 1399.68   186.3 1399.59   189.3 1399.71   192.4 1401.21   195.5 1402.93
   198.6 1404.03   210.9 1403.69   220.1 1404.04   229.3 1404.93   314.4 1404.53
     336 1404.09   371.1 1404.31     386 1404.79   396.4 1404.26   486.9  1404.9
   517.1 1404.34   616.3 1405.03   629.3 1404.79   655.4 1405.95     678 1407.86
#Mann= 5 ,-1,0
       0     .06       0  143.93     .05       0180.9983    .045       0
   192.4     .05       0  253.93      .1       0
Bank Sta=180.9983,192.4
XS Rating Curve= 0 ,0
Exp/Cntr(USF)=0,0
Exp/Cntr=0.3,0.1
LCMann Table=0

Chan Stop Cuts=-1
Use User Specified Reach Order=0
Composite Channel Slope=5